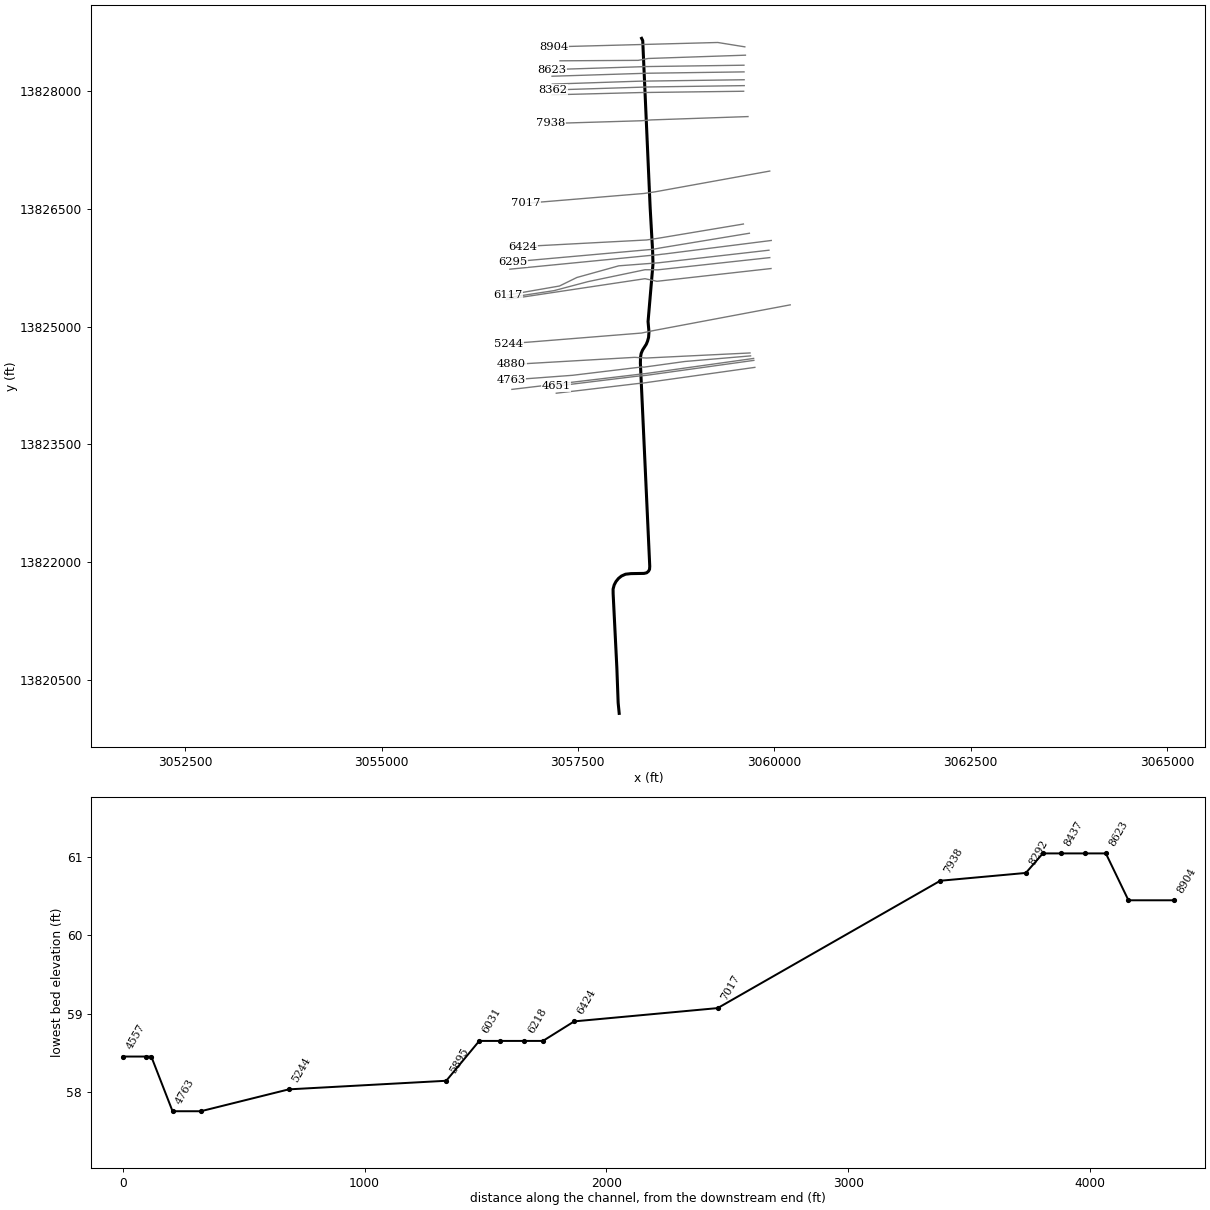
--- D124-00-00.prj (project) ---

Proj Title=D124-00-00
Current Plan=p01
Default Exp/Contr=.3,.1
English Units
Geom File=g01
Geom File=g03
Flow File=f03
Flow File=f04
Plan File=p01
Plan File=p04
Y Axis Title=Elevation
X Axis Title(PF)=Main Channel Distance
X Axis Title(XS)=Station
BEGIN DESCRIPTION:
Brays Bayou Watershed
Tributary 22.69
HCFCD Unit D124-00-00
Flood Hazard & Floodway Model
10, 2, 1, 0.2% Event
Filename D124.prj
Prepared by: Dodson & Associates, Inc.   Date: December 2003
Reviewed by:____________________	 Date:_________
STATUS (Final RAS)
FOR FLOOD HARZARD RECOVERY DATA ONLY,03/02/2004
Will Be Voided Upon Release of The Preliminary DFIRM
END DESCRIPTION:
DSS Export Rating Curves= 0
DSS Export Rating Curve Sorted= 0
DSS Export Volume Flow Curves= 0
DXF OffsetX= 0
DXF OffsetY= 0
DXF ScaleX= 1
DXF ScaleY= 10

--- D124-00-00.p01 (plan) ---

Plan Title=FEMA Effective June 2007
Version=Version 3.0.1  Mar 2001
Short Identifier=FEMAeff0607
Geom File=g01
Flow File=f03
Subcritical Flow
K Sum by GR= 0
Std Step Tol= 0.01
Critical Tol= 0.01
Num of Std Step Trials= 20
Max Error Tol= 0.3
Flow Tol Ratio= 0.001
Split Flow NTrial= 30
Split Flow Tol= 0.02
Split Flow Ratio= 0.02
Log Output Level= 0
Friction Slope Method= 1
Unsteady Friction Slope Method= 2
Parabolic Critical Depth
Global Vel Dist= 0 , 0 , 0
Global Log Level= 0
CheckData=True
Encroach Param=-1 ,0,0, 0
Computation Interval=1HOUR
Output Interval=1HOUR
Run HTab= 0
Run UNet= 0
Run PostProcess= 0
UNET Theta= 1
UNET ZTol= 0.02
UNET ZSATol= 0.1
UNET MxIter= 20
UNET MaxInSteps= 20
UNET DtIC= 0
UNET DtMin= 0
UNET MaxCRTS= 20
UNET WFStab= 2
UNET SFStab= 1
UNET WFX= 1
UNET SFX= 1
UNET Convert EG Bridges=-1
UNET Use Existing IB Tables=-1
Instantaneous Interval=1HOUR
Write IC File= 0
Write Velocity= 0
Write Detailed= 0

--- D124-00-00.p04 (plan) ---

Plan Title=Floodway
Version=Version 3.0.1  Mar 2001
Short Identifier=Floodway0607
Geom File=g01
Flow File=f04
Subcritical Flow
K Sum by GR= 0
Std Step Tol= 0.01
Critical Tol= 0.01
Num of Std Step Trials= 20
Max Error Tol= 0.3
Flow Tol Ratio= 0.001
Split Flow NTrial= 30
Split Flow Tol= 0.02
Split Flow Ratio= 0.02
Log Output Level= 0
Friction Slope Method= 1
Unsteady Friction Slope Method= 2
Parabolic Critical Depth
Global Vel Dist= 0 , 0 , 0
Global Log Level= 0
CheckData=True
Encroach Param=-1 ,0,0, 2
Encroach River=D124-00-00
Encroach Reach=Reach 0
Encroach Node=8716
       1 1260.83 1347.84
Encroach Node=8623
       1 1208.34  1343.8
Encroach Node=8537
       1 1198.95 1349.14
Encroach Node=8492
       1 1198.95 1349.14
Encroach Node=8437
       1 1200.34  1335.8
Encroach Node=8362
       1 1216.38 1336.54
Encroach Node=8292
       1    1209 1302.92
Encroach Node=7938
       1  1249.9 1370.27
Encroach Node=7017
       1 1502.93 1605.88
Encroach Node=6424
       1  1130.3  1230.7
Encroach Node=6295
       1 1192.94    1314
Encroach Node=6218
       1 1436.68 1587.35
Encroach Node=6170
       1 1429.78 1587.35
Encroach Node=6117
       1 1429.78 1543.45
Encroach Node=6031
       1 1432.24 1555.45
Encroach Node=5895
       1 1473.74 1582.48
Encroach Node=5244
       1 1787.82 1889.43
Encroach Node=4880
       1 1345.93 1450.73
Encroach Node=4763
       1 1355.93 1460.73
Encroach Node=4675
       1 1378.88 1514.84
Encroach Node=4661
       1 1377.44 1514.84
Encroach Node=4651
       1 1377.44  1503.1
Encroach Node=4557
       1 1377.06 1515.82
Encroach Node=4449
       1  1407.7 1522.27
Encroach Node=4302
       1 1227.32 1344.22
Encroach Node=4197
       1 1258.49 1377.22
Encroach Node=4147
       1 1087.32 1377.22
Encroach Node=4114
       1 1087.32 1204.22
Encroach Node=4021
       1 1245.32 1362.22
Encroach Node=3931
       1 1428.29 1541.83
Encroach Node=3682
       1 1402.74  1514.6
Encroach Node=2448
       1 1786.16  1896.9
Encroach Node=1379
       1 1722.66 1828.68
Encroach Node=510
       1 1712.39 1825.63
Encroach Node=95
       1 1760.96 1880.15
Encroach Node=93
       1 1760.96 1880.15
Encroach Node=91
       1 1760.96 1880.15
Encroach Reach=D124-00-00
Encroach Node=8904
       1 1244.29 1369.25
Encroach Node=8716
       1 1260.83 1347.84
Encroach Node=8623
       1 1208.34  1343.8
Encroach Node=8537
       1 1198.95 1349.14
Encroach Node=8492
       1 1198.95 1349.14
Encroach Node=8437
       1 1200.34  1335.8
Encroach Node=8362
       1 1216.38 1336.54
Encroach Node=8292
       1    1209 1302.92
Encroach Node=7938
       1  1249.9 1370.27
Encroach Node=7017
       1 1502.93 1605.88
Encroach Node=6424
       1  1130.3  1230.7
Encroach Node=6295
       1 1192.94    1314
Encroach Node=6218
       1 1436.68 1587.35
Encroach Node=6170
       1 1429.78 1587.35
Encroach Node=6117
       1 1429.78 1543.45
Encroach Node=6031
       1 1432.24 1555.45
Encroach Node=5895
       1 1473.74 1582.48
Encroach Node=5244
       1 1787.82 1889.43
Encroach Node=4880
       1 1345.93 1450.73
Encroach Node=4763
       1 1355.93 1460.73
Encroach Node=4675
       1 1378.88 1514.84
Encroach Node=4661
       1 1377.44 1514.84
Encroach Node=4651
       1 1377.44  1503.1
Encroach Node=4557
       1 1377.06 1515.82
Encroach Node=4449
       1  1407.7 1522.27
Encroach Node=4302
       1 1227.32 1344.22
Encroach Node=4197
       1 1258.49 1377.22
Encroach Node=4147
       1 1087.32 1377.22
Encroach Node=4114
       1 1087.32 1204.22
Encroach Node=4021
       1 1245.32 1362.22
Encroach Node=3931
       1 1428.29 1541.83
Encroach Node=3682
       1 1402.74  1514.6
Encroach Node=2448
       1 1786.16  1896.9
Encroach Node=1379
       1 1722.66 1828.68
Encroach Node=510
       1 1712.39 1825.63
Encroach Node=95
       1 1760.96 1880.15
Encroach Node=93
       1 1760.96 1880.15
Encroach Node=91
       1 1760.96 1880.15
Encroach Reach=D124-00-00_0001
Encroach Node=8904
       1 1244.29 1369.25
Encroach Node=8716
       1 1260.83 1347.84
Encroach Node=8623
       1 1208.34  1343.8
Encroach Node=8537
       1 1198.95 1349.14
Encroach Node=8492
       1 1198.95 1349.14
Encroach Node=8437
       1 1200.34  1335.8
Encroach Node=8362
       1 1216.38 1336.54
Encroach Node=8292
       1    1209 1302.92
Encroach Node=7938
       1  1249.9 1370.27
Encroach Node=7017
       1 1502.93 1605.88
Encroach Node=6424
       1  1130.3  1230.7
Encroach Node=6295
       1 1192.94    1314
Encroach Node=6218
       1 1436.68 1587.35
Encroach Node=6170
       1 1429.78 1587.35
Encroach Node=6117
       1 1429.78 1543.45
Encroach Node=6031
       1 1432.24 1555.45
Encroach Node=5895
       1 1473.74 1582.48
Encroach Node=5244
       1 1787.82 1889.43
Encroach Node=4880
       1 1345.93 1450.73
Encroach Node=4763
       1 1355.93 1460.73
Encroach Node=4675
       1 1378.88 1514.84
Encroach Node=4661
       1 1377.44 1514.84
Encroach Node=4651
       1 1377.44  1503.1
Encroach Node=4557
       1 1377.06 1515.82
Encroach Node=4449
       1  1407.7 1522.27
Encroach Node=4302
       1 1227.32 1344.22
Encroach Node=4197
       1 1258.49 1377.22
Encroach Node=4147
       1 1087.32 1377.22
Encroach Node=4114
       1 1087.32 1204.22
Encroach Node=4021
       1 1245.32 1362.22
Encroach Node=3931
       1 1428.29 1541.83
Encroach Node=3682
       1 1402.74  1514.6
Encroach Node=2448
       1 1786.16  1896.9
Encroach Node=1379
       1 1722.66 1828.68
Encroach Node=510
       1 1712.39 1825.63
Encroach Node=95
       1 1760.96 1880.15
Encroach Node=93
       1 1760.96 1880.15
Encroach Node=91
       1 1760.96 1880.15
Computation Interval=1HOUR
Output Interval=1HOUR
Run HTab= 0
Run UNet= 0
Run PostProcess= 0
UNET Theta= 1
UNET ZTol= 0.02
UNET ZSATol= 0.1
UNET MxIter= 20
UNET MaxInSteps= 20
UNET DtIC= 0
UNET DtMin= 0
UNET MaxCRTS= 20
UNET WFStab= 2
UNET SFStab= 1
UNET WFX= 1
UNET SFX= 1
UNET Convert EG Bridges=-1
UNET Use Existing IB Tables=-1
Instantaneous Interval=1HOUR
Write IC File= 0
Write Velocity= 0
Write Detailed= 0

--- D124-00-00.f03 (steady flow) ---

Flow Title=FEMA Effective June 2007
Version=Version 3.0.1  Mar 2001
Number of Profiles= 4
Profile Names=10PCT_10yr,2PCT_50yr,1PCT_100yr,0.2PCT_500yr
River Rch & RM=D124-00-00,D124-00-00_0001 ,8904
     804    1153    1332    1824
River Rch & RM=D124-00-00,D124-00-00_0001 ,8292
     889    1279    1479    2029
River Rch & RM=D124-00-00,D124-00-00_0001 ,7017
     972    1402    1621    2229
River Rch & RM=D124-00-00,D124-00-00_0001 ,5895
    1054    1522    1762    2426
River Rch & RM=D124-00-00,D124-00-00_0001 ,4880
    1160    1678    1943    2681
River Rch & RM=D124-00-00,D124-00-00_0001 ,3682
    1279    1856    2150    2971
River Rch & RM=D124-00-00,D124-00-00_0001 ,2448
    1393    2024    2347    3249
River Rch & RM=D124-00-00,D124-00-00_0001 ,1379
    1492    2173    2520    3493
River Rch & RM=D124-00-00,D124-00-00_0001 ,510
    1554    2265    2627    3645
Boundary for River Rch & Prof#=D124-00-00,D124-00-00_0001 , 1
Up Type= 0
Dn Type= 3
Dn Slope=.002
Boundary for River Rch & Prof#=D124-00-00,D124-00-00_0001 , 2
Up Type= 0
Dn Type= 3
Dn Slope=.002
Boundary for River Rch & Prof#=D124-00-00,D124-00-00_0001 , 3
Up Type= 0
Dn Type= 3
Dn Slope=.002
Boundary for River Rch & Prof#=D124-00-00,D124-00-00_0001 , 4
Up Type= 0
Dn Type= 3
Dn Slope=.002
DSS Import GetInterval= 0
DSS Import GetPeak= 0
DSS Import FillOption= 0

--- D124-00-00.f04 (steady flow) ---

Flow Title=Floodway
Version=Version 3.0.1  Mar 2001
Number of Profiles= 2
Profile Names=1PCT_100yr,1PCTFloodway_100yrFW
River Rch & RM=D124-00-00,D124-00-00_0001 ,8904
    1332    1332
River Rch & RM=D124-00-00,D124-00-00_0001 ,8292
    1479    1479
River Rch & RM=D124-00-00,D124-00-00_0001 ,7017
    1621    1621
River Rch & RM=D124-00-00,D124-00-00_0001 ,5895
    1762    1762
River Rch & RM=D124-00-00,D124-00-00_0001 ,4880
    1943    1943
River Rch & RM=D124-00-00,D124-00-00_0001 ,3682
    2150    2150
River Rch & RM=D124-00-00,D124-00-00_0001 ,2448
    2347    2347
River Rch & RM=D124-00-00,D124-00-00_0001 ,1379
    2520    2520
River Rch & RM=D124-00-00,D124-00-00_0001 ,510
    2627    2627
Boundary for River Rch & Prof#=D124-00-00,D124-00-00_0001 , 1
Up Type= 0
Dn Type= 1
Dn Known WS=60.34
Boundary for River Rch & Prof#=D124-00-00,D124-00-00_0001 , 2
Up Type= 0
Dn Type= 1
Dn Known WS=60.34
DSS Import GetInterval= 0
DSS Import GetPeak= 0
DSS Import FillOption= 0

--- D124-00-00.g01 (geometry) ---

Geom Title=D124-00-00 June 2007
Version=Version 3.0.1  Mar 2001

River Reach=D124-00-00      ,D124-00-00_0001
Reach XY= 30
      3058311.73     13828671.73     3058326.127    13828642.443
     3058420.484    13826518.594     3058451.936    13825964.043
     3058456.902    13825800.161     3058393.998    13825065.173
     3058405.585    13824932.743     3058400.619    13824863.217
     3058387.376    13824815.211     3058370.822    13824775.482
     3058324.472    13824702.646     3058306.263    13824659.606
     3058297.986    13824609.944      3058296.33    13824533.797
     3058415.518    13821949.754     3058412.688    13821909.712
     3058399.722    13821886.036     3058376.609    13821866.305
     3058342.785    13821858.413     3058175.599    13821855.536
     3058107.135    13821847.928     3058055.787    13821825.107
     3058017.751    13821794.679     3057985.421    13821754.741
       3057962.6       13821711.     3057948.701    13821658.407
     3057949.287    13821600.697     3057996.707    13820655.249
     3058013.261    13820209.953     3058026.439    13820075.965

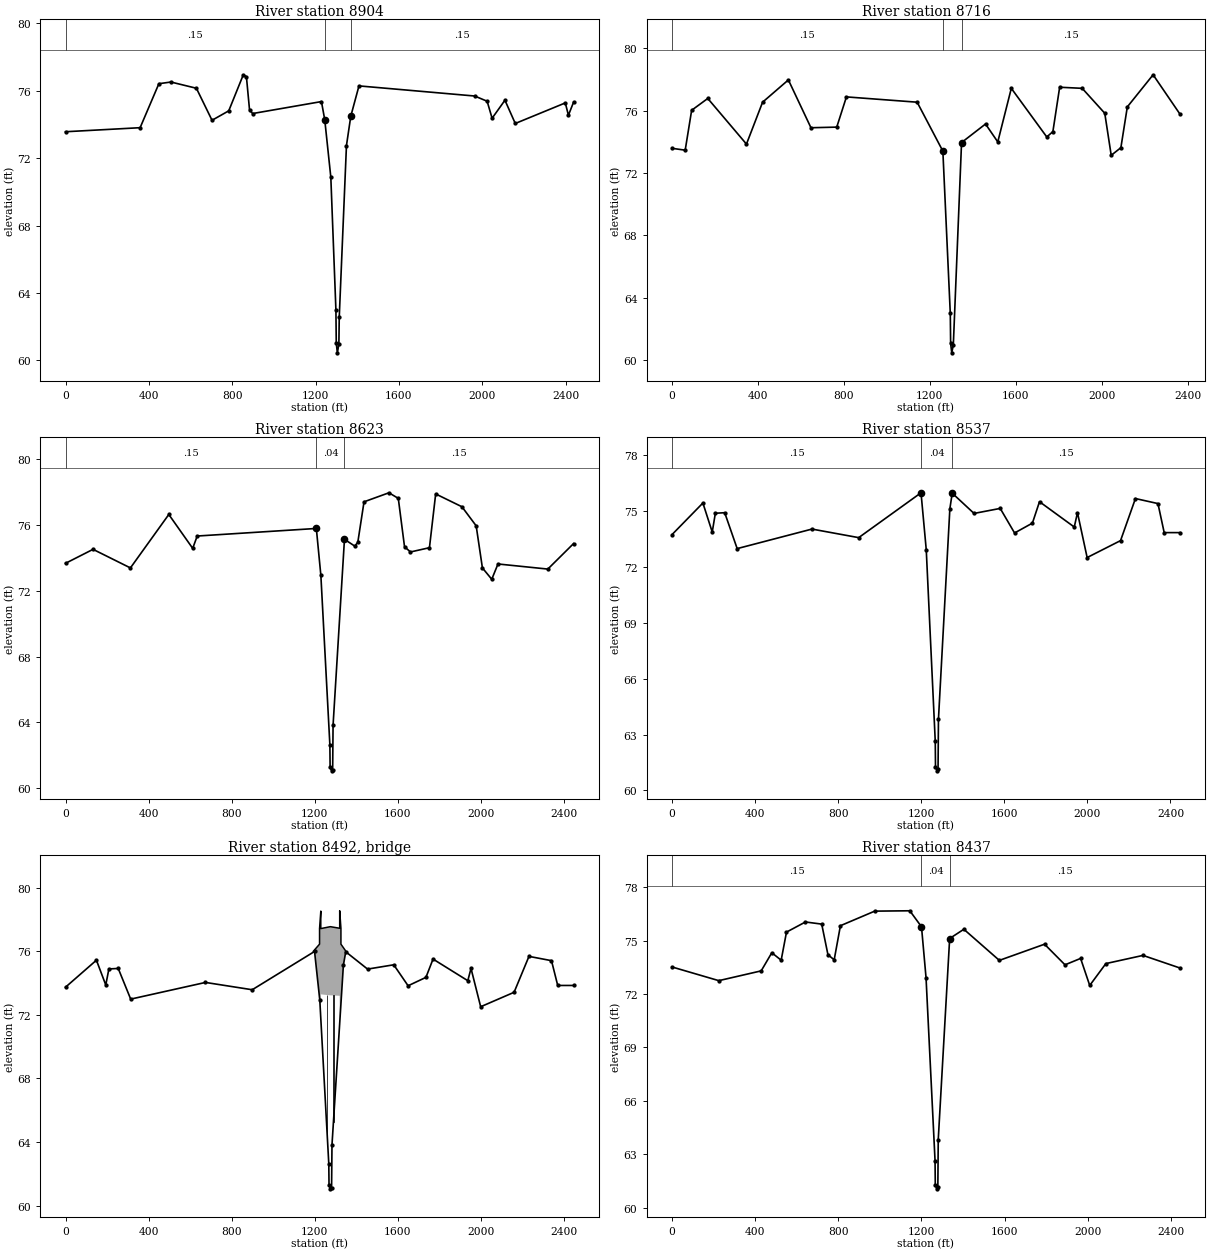
Type RM Length L Ch R = 1 ,8904    ,181.16,187.91,212.38
BEGIN DESCRIPTION:
Added Cross Section to Match LODS
END DESCRIPTION:
XS GIS Cut Line= 3
      3059626.19    13828563.345     3059281.504    13828618.822
     3057192.926    13828563.345
#Sta/Elev= 30
       0   73.57  358.13   73.81  448.16   76.42  506.03   76.52  628.23   76.15
  703.25   74.25  783.49   74.81  853.31   76.95  868.31   76.84  883.32   74.86
  898.32   74.65 1228.44   75.36 1244.29   74.28 1273.45   70.87 1297.91   62.98
 1299.52   61.05 1304.73   60.45 1312.06   60.96 1313.88   62.57 1348.48   72.75
 1369.25   74.49  1408.5   76.29  1963.7   75.69 2023.72   75.38  2047.5   74.37
 2109.16   75.44 2158.77   74.06 2398.85   75.28 2413.86   74.55 2438.44   75.32
#Mann= 3 , 0 , 0
       0     .15       0 1244.29     .04       0 1369.25     .15       0
#XS Ineff= 2 , 0
       0 1233.44         1393.49       0
Permanent Ineff=
       T       T
Bank Sta=1244.29,1369.25
XS Rating Curve= 0
Exp/Cntr=.3,.1

Type RM Length L Ch R = 1 ,8716    ,104.55,93.47,83.01
BEGIN DESCRIPTION:
8716.088  Survey
END DESCRIPTION:
XS GIS Cut Line= 4
     3059634.009    13828457.249     3058396.199    13828415.177
     3058268.484    13828391.347      3057272.27    13828385.583
#Sta/Elev= 30
       0   73.58   61.54   73.46   91.56   76.02  166.61   76.78  346.71   73.85
  421.75   76.54  541.82   77.97  646.88    74.9  766.95   74.94  811.98   76.88
 1141.18   76.54 1260.83    73.4 1295.41   62.98 1297.02   61.05 1302.23   60.45
 1309.56   60.96 1347.84   73.95 1459.43   75.14 1516.44   73.99 1579.43   77.43
 1744.43   74.31 1772.93   74.65 1804.44    77.5 1909.44   77.43 2014.44   75.83
 2044.44   73.13 2089.44   73.62 2119.44   76.24 2239.44    78.3 2364.67   75.77
#Mann= 3 , 0 , 0
       0     .15       0 1260.83     .04       0 1347.84     .15       0
#XS Ineff= 2 , 0
       0    1220            1378       0
Permanent Ineff=
       T       T
Bank Sta=1260.83,1347.84
XS Rating Curve= 0
Exp/Cntr=.3,.1

Type RM Length L Ch R = 1 ,8623    ,85,85.11,85.01
BEGIN DESCRIPTION:
8622.620  Copied Survey
END DESCRIPTION:
XS GIS Cut Line= 6
      3059615.14      13828329.5      3058404.73     13828312.67
     3058392.986     13828312.21     3058339.503     13828312.77
     3058326.619      13828310.6     3057168.676     13828274.05
#Sta/Elev= 30
       0   73.67  132.65   74.52  312.67   73.39  497.61   76.64   612.7   74.58
  634.52   75.33 1208.34   75.79 1230.16   72.93 1273.52   62.63 1274.67   61.27
 1281.51   61.05 1286.96   61.13  1288.9   63.82  1343.8   75.13    1393   74.72
    1408   74.94 1438.02   77.41 1558.08   77.96  1603.1   77.62 1633.12   74.68
 1661.67   74.36 1753.18   74.62 1783.19   77.89 1909.66   77.11 1978.29   75.95
 2008.31   73.39 2053.33    72.7 2083.34   73.63 2323.46   73.32 2447.35   74.87
#Mann= 3 , 0 , 0
       0     .15       0 1208.34     .04       0  1343.8     .15       0
#XS Ineff= 2 , 0
       0    1197            1360       0
Permanent Ineff=
       T       T
Bank Sta=1208.34,1343.8
XS Rating Curve= 0
Exp/Cntr=.5,.3

Type RM Length L Ch R = 1 ,8537    ,99.91,100.65,98.24
BEGIN DESCRIPTION:
8537.511  Copied Survey
END DESCRIPTION:
XS GIS Cut Line= 6
      3059616.33     13828244.51     3058407.012      13828227.7
     3058394.227     13828227.19     3058346.158      13828227.7
     3058333.017     13828225.75     3057171.372     13828189.09
#Sta/Elev= 30
       0   73.74  148.84   75.44  193.85   73.88  208.85   74.89  253.85   74.92
  313.86   72.99   673.9   74.04  898.92   73.58 1198.95   75.99 1224.16   72.93
 1267.52   62.63 1268.67   61.27 1275.51   61.05 1280.96   61.13  1282.9   63.82
  1337.8   75.13 1349.14   75.97  1454.2   74.88 1580.22   75.15  1649.3   73.83
 1735.22   74.36 1769.36   75.51 1936.71   74.15 1952.21   74.92  1998.7   72.51
 2159.55   73.42 2231.19   75.68 2339.64   75.41 2369.66   73.85 2445.82   73.85
#Mann= 3 , 0 , 0
       0     .15       0 1198.95     .04       0 1349.14     .15       0
#XS Ineff= 2 , 0
       0    1191            1361       0
Permanent Ineff=
       T       T
Bank Sta=1198.95,1349.14
XS Rating Curve= 0
Exp/Cntr=.5,.3

Type RM Length L Ch R = 3 ,8492    ,,,
BEGIN DESCRIPTION:
Richmond Blvd.
END DESCRIPTION:
Bridge Culvert--1,0,-1,-1, 0
Deck Dist Width WeirC Skew NumUp NumDn MinLoCord MaxHiCord MaxSubmerge Is_Ogee
5.65,85,2.6,0, 11, 11, , , .95, 0, 0,0,,
    1193    1223    1223    1229    1229    1275    1320    1320    1326    1326
    1350
      76   76.45   77.43   78.53   77.43   77.55   77.45   78.55   77.45   76.45
      76
                                   73.29   73.23    73.2
        
    1189    1223    1223    1229    1229    1275    1320    1320    1326    1326
    1350
    75.9   76.45   77.43   78.53   77.43   77.55   77.45   78.55   77.45   76.45
    75.9
                                   73.29   73.23    73.2
        
Pier Skew, UpSta & Num, DnSta & Num=  ,1260, 2 ,1258, 2 , 0 , 0 , 0 ,,
    1.35    1.35
       0     100
    1.35    1.35
       0     100
Pier Skew, UpSta & Num, DnSta & Num=  ,1290, 2 ,1288, 2 , 0 , 0 , 0 ,,
    1.35    1.35
       0     100
    1.35    1.35
       0     100
BR Coef=-1 , 1 , 1 ,1.25, 0 ,,,.8,-1,2,0,
WSPro=,,,, 1 ,,,, 0 ,,,, 0 ,,,,-1 ,-1 ,-1 , 0 , 0 , 0 , 0 , 0
BC Design=,, 0 ,, 0 ,,,,,,

Type RM Length L Ch R = 1 ,8437    ,75.15,74.77,76.76
BEGIN DESCRIPTION:
8436.864  Survey
END DESCRIPTION:
XS GIS Cut Line= 4
     3059617.721    13828144.522     3058409.695    13828127.833
     3058282.048    13828126.085     3057174.542    13828089.144
#Sta/Elev= 30
       0   73.53  225.24   72.76  429.17   73.31  480.27   74.33  525.27   73.91
  550.86   75.49  642.13   76.06  720.29   75.94  750.29   74.22   780.3   73.93
   810.3   75.85  975.31   76.67 1144.11   76.69 1200.34   75.79 1222.16   72.93
 1265.52   62.63 1266.67   61.27 1273.51   61.05 1278.96   61.13  1280.9   63.82
  1335.8   75.13 1404.08   75.65 1574.86    73.9 1792.23   74.81 1890.66   73.65
  1965.7   74.01  2009.6   72.49 2087.23   73.72 2265.86   74.18 2443.92   73.47
#Mann= 3 , 0 , 0
       0     .15       0 1200.34     .04       0  1335.8     .15       0
#XS Ineff= 2 , 0
       0    1184            1354       0
Permanent Ineff=
       T       T
Bank Sta=1200.34,1335.8
XS Rating Curve= 0
Exp/Cntr=.5,.3

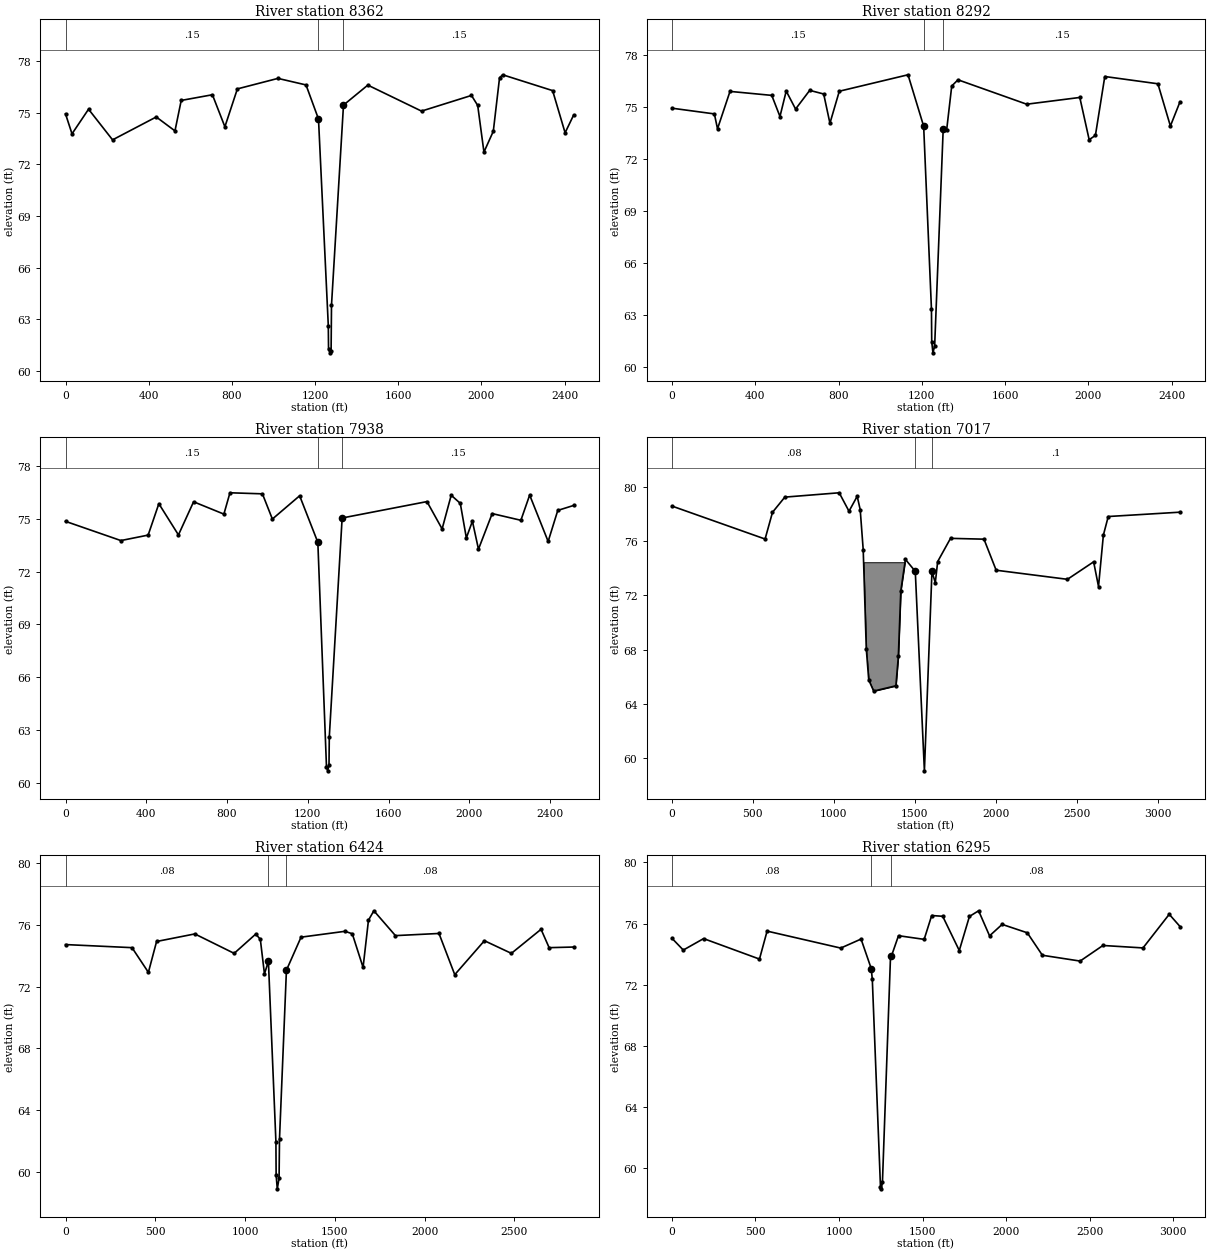
Type RM Length L Ch R = 1 ,8362    ,70.07,70.37,68.1
BEGIN DESCRIPTION:
8362.093  Copied Survey
END DESCRIPTION:
XS GIS Cut Line= 6
      3059618.76     13828069.53      3058411.71     13828052.75
     3058396.783     13828052.15     3058359.858     13828052.54
     3058351.057     13828051.06     3057176.921     13828014.18
#Sta/Elev= 30
       0   74.93   31.26   73.77  110.78    75.2  226.28   73.42   436.3   74.75
  526.31   73.94  556.31   75.71  706.33   76.04  766.33   74.18  826.34   76.38
 1021.36   76.99 1156.37   76.61 1216.38   74.63 1263.52   62.63 1264.67   61.27
 1271.51   61.05 1276.96   61.13  1278.9   63.82 1336.54   75.44 1453.56    76.6
 1711.73   75.09 1951.85      76 1981.86   75.42 2011.88   72.71  2056.9   73.92
 2086.92   77.03 2101.92    77.2 2342.05   76.28 2402.08   73.83 2442.68   74.85
#Mann= 3 , 0 , 0
       0     .15       0 1216.38     .04       0 1336.54     .15       0
#XS Ineff= 2 , 0
       0    1180            1347       0
Permanent Ineff=
       T       T
Bank Sta=1216.38,1336.54
XS Rating Curve= 0
Exp/Cntr=.3,.1

Type RM Length L Ch R = 1 ,8292    ,348.51,353.82,359.49
BEGIN DESCRIPTION:
8291.723  Survey
END DESCRIPTION:
XS GIS Cut Line= 4
     3059611.206    13827997.932     3058420.352    13827982.957
     3058291.979    13827981.223     3057171.285    13827952.326
#Sta/Elev= 30
       0   74.93  203.72    74.6  218.72   73.74  278.73    75.9  479.34   75.67
  518.75   74.45  548.75   75.92  593.75   74.88  661.65   75.96  728.76   75.75
  758.77   74.06  803.77   75.91  1133.8   76.86    1209   73.89 1246.44   63.32
 1247.72   61.45 1253.54    60.8  1261.8   61.19 1302.92   73.75 1319.33   73.66
 1343.82   76.21 1373.83   76.57 1703.94   75.16 1959.02   75.55 2004.04   73.11
 2034.05   73.36 2079.06   76.76 2334.15   76.34 2394.17    73.9  2440.4    75.3
#Mann= 3 , 0 , 0
       0     .15       0    1209     .04       0 1302.92     .15       0
#XS Ineff= 2 , 0
       0    1169            1331       0
Permanent Ineff=
       T       T
Bank Sta=1209,1302.92
XS Rating Curve= 0
Exp/Cntr=.3,.1

Type RM Length L Ch R = 1 ,7938    ,904.11,920.73,928.05
BEGIN DESCRIPTION:
7937.904  Survey
END DESCRIPTION:
XS GIS Cut Line= 4
     3059666.585    13827675.432     3058433.062    13827632.825
     3058306.995    13827622.176     3057151.739    13827587.478
#Sta/Elev= 30
       0   74.85  274.25   73.76  409.33   74.07  462.39   75.85  559.42   74.08
  634.46   75.96  784.55   75.26  814.57   76.47  975.41   76.41  1024.7   74.98
 1159.78    76.3  1249.9   73.66 1292.67   60.94 1298.52    60.7  1305.2   61.02
 1306.64   62.62 1370.27   75.04 1790.46   75.97  1865.5   74.42 1910.52   76.33
 1955.54   75.87 1985.55   73.91 2015.56   74.86 2045.58   73.27 2113.53   75.29
 2255.67   74.91 2299.19   76.34 2390.73   73.71 2438.43   75.47 2516.55   75.75
#Mann= 3 , 0 , 0
       0     .15       0  1249.9     .04       0 1370.27     .15       0
#XS Ineff= 2 , 0
       0    1205            1371       0
Permanent Ineff=
       T       T
Bank Sta=1249.9,1370.27
XS Rating Curve= 0
Exp/Cntr=.3,.1

Type RM Length L Ch R = 1 ,7017    ,594.89,593.21,592.27
BEGIN DESCRIPTION:
7017.172  Survey
END DESCRIPTION:
XS GIS Cut Line= 4
     3059943.478    13826981.569     3058484.316    13826717.312
     3058342.201    13826696.267     3056835.755    13826571.115
#Sta/Elev= 30
       0   78.59  575.18   76.16  620.92   78.13  697.14   79.25 1032.92   79.57
 1093.48   78.21  1144.1   79.31 1162.72   78.33 1181.33   75.36 1200.19   68.07
 1215.43   65.77 1245.92   64.95 1383.12   65.34 1398.36   67.51  1413.6   72.35
 1441.95   74.66 1502.93   73.78 1559.27   59.07 1605.88   73.77 1626.56   72.94
 1641.31    74.5 1720.61   76.21  1927.3   76.15 2002.55   73.86 2442.88   73.19
 2604.62   74.48 2634.73   72.66 2664.83   76.45 2694.93   77.82  3138.2   78.14
#Mann= 3 , 0 , 0
       0     .08       0 1502.93     .04       0 1605.88      .1       0
#XS Ineff= 2 , 0
       0    1208            1657       0
Permanent Ineff=
       T       T
#Block Obstruct= 1 ,-1
 1160.68 1442.54   74.45
Bank Sta=1502.93,1605.88
XS Rating Curve= 0
Exp/Cntr=.3,.1

Type RM Length L Ch R = 1 ,6424    ,127.6,129.2,126.42
BEGIN DESCRIPTION:
6423.961  Survey
END DESCRIPTION:
XS GIS Cut Line= 4
     3059607.949    13826307.252     3058514.793    13826124.713
      3058374.03    13826104.122     3056796.664    13826020.586
#Sta/Elev= 30
       0   74.73  370.51   74.53  461.75   72.93  507.38   74.93  720.29   75.42
  939.58   74.16 1059.71   75.41 1085.27   75.07 1108.29   72.83  1130.3   73.65
 1172.14   61.95  1173.3   59.79  1179.7    58.9 1189.71   59.59  1192.1   62.14
  1230.7   73.07 1312.17   75.21  1557.1   75.59 1597.57   75.43 1657.65   73.25
 1687.69   76.31 1717.74   76.92  1837.9   75.31 2080.51   75.45 2168.37   72.78
  2333.6   74.98 2483.81   74.16 2649.04   75.72  2694.1   74.53 2830.13   74.57
#Mann= 3 , 0 , 0
       0     .08       0  1130.3     .04       0  1230.7     .08       0
#XS Ineff= 2 , 0
       0     669            1366       0
Permanent Ineff=
       T       T
Bank Sta=1130.3,1230.7
XS Rating Curve= 0
Exp/Cntr=.3,.1

Type RM Length L Ch R = 1 ,6295    ,85.17,76.47,75.25
BEGIN DESCRIPTION:
6294.759  Copied Survey
END DESCRIPTION:
XS GIS Cut Line= 6
      3059684.34     13826189.84     3058545.438     13826001.93
     3058524.564      13825997.6      3058464.43    13825987.133
     3058430.715     13825983.11      3056666.83     13825825.37
#Sta/Elev= 30
       0   75.04   67.75   74.27  189.37   75.02  523.85   73.68  569.46   75.51
 1010.36    74.4 1131.97   74.99 1192.94   73.06 1199.38   72.35 1248.28   58.78
 1253.14   58.65    1260   59.08 1308.45   73.87    1314   73.88 1356.18   75.21
 1509.78   74.97 1554.96   76.53 1620.81   76.48 1720.04   74.24 1780.86   76.47
 1835.81   76.84 1901.34    75.2 1976.64   75.95 2127.24    75.4  2217.6   73.93
 2443.49   73.55 2580.06   74.57 2819.99   74.41    2977   76.61 3041.54   75.81
#Mann= 3 , 0 , 0
       0     .08       0 1192.94     .04       0    1314     .08       0
#XS Ineff= 2 , 0
       0     721            1423       0
Permanent Ineff=
       T       T
Bank Sta=1192.94,1314
XS Rating Curve= 0
Exp/Cntr=.5,.3

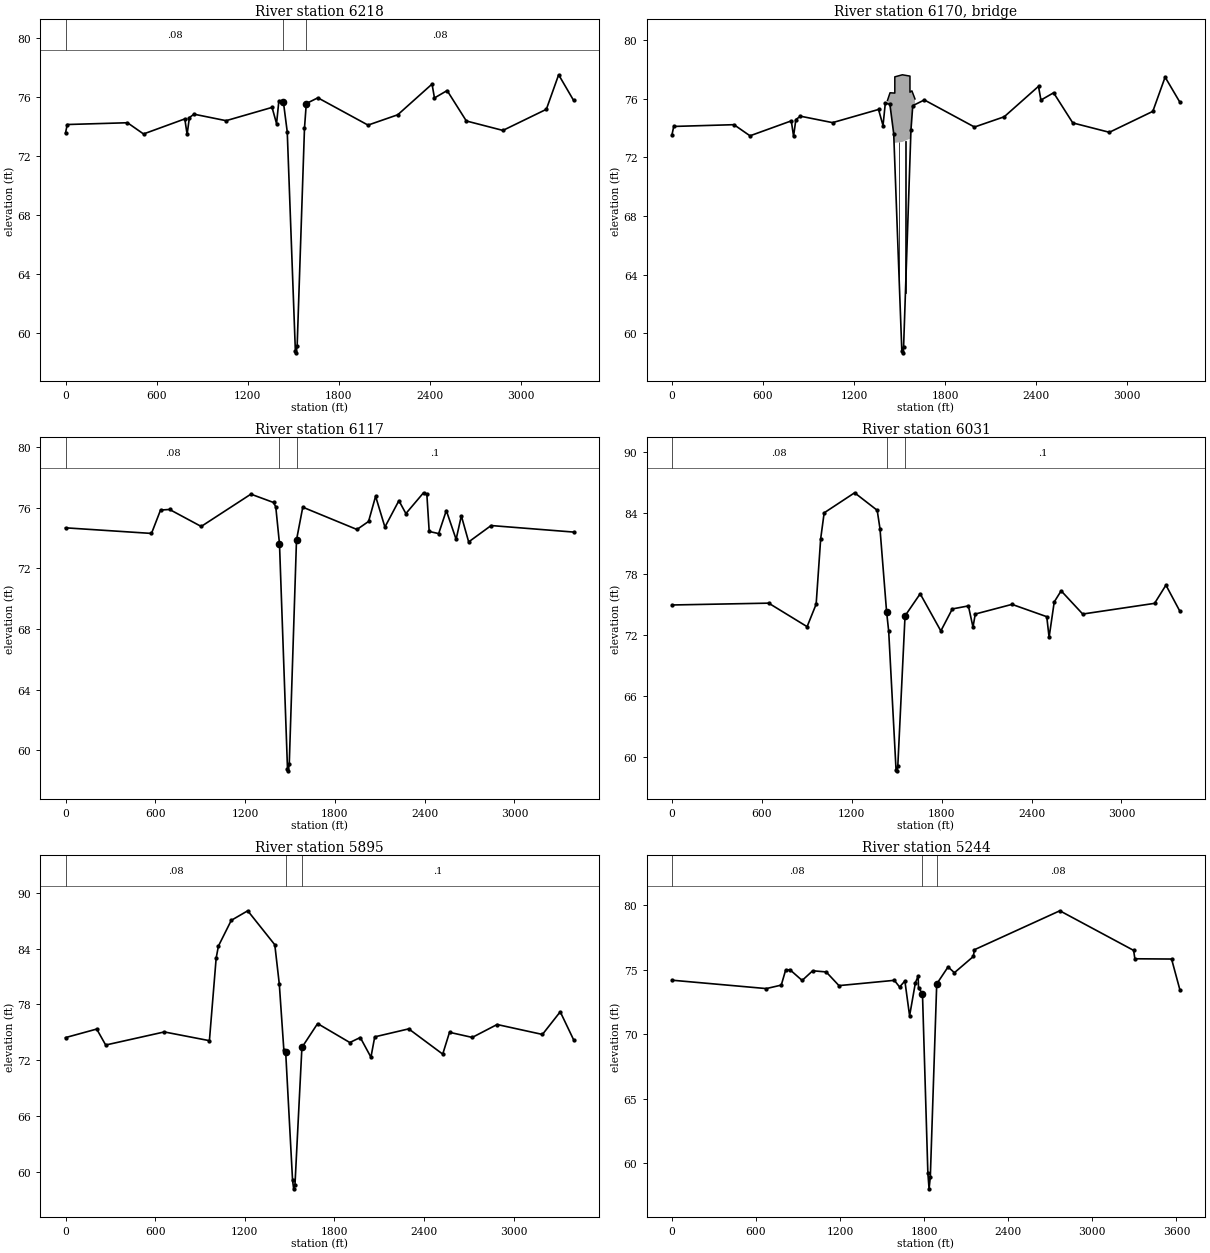
Type RM Length L Ch R = 1 ,6218    ,103.33,101.73,100.22
BEGIN DESCRIPTION:
6218.284  Copied Survey
END DESCRIPTION:
XS GIS Cut Line= 6
     3059962.801    13826097.675      3058599.03    13825925.207
      3058585.86    13825924.323     3058520.891     13825915.84
     3058408.029    13825905.943     3056634.036    13825732.223
#Sta/Elev= 30
       0   73.55   11.68   74.12  408.53   74.24  514.37   73.48  786.52    74.5
  801.64   73.45  816.75   74.59  846.99   74.82 1058.67   74.38 1361.74   75.28
  1391.3   74.18 1406.43   75.71 1436.68   75.63 1461.78   73.62 1515.28   58.78
 1520.14   58.65    1527   59.08 1575.45   73.87 1587.35   75.54 1663.73   75.93
 1994.29   74.08 2190.22   74.78  2416.3   76.86 2432.29   75.92 2515.83   76.42
 2642.38   74.36 2883.52   73.72 3169.89   75.15 3250.97   77.49  3349.2   75.76
#Mann= 3 , 0 , 0
       0     .08       0 1436.68     .04       0 1587.35     .08       0
#XS Ineff= 2 , 0
       0     980            1682       0
Permanent Ineff=
       T       T
Bank Sta=1436.68,1587.35
XS Rating Curve= 0
Exp/Cntr=.5,.3

Type RM Length L Ch R = 3 ,6170    ,,,
BEGIN DESCRIPTION:
Westpark Blvd.
END DESCRIPTION:
Bridge Culvert--1,0,-1,-1, 0
Deck Dist Width WeirC Skew NumUp NumDn MinLoCord MaxHiCord MaxSubmerge Is_Ogee
10,85,2.6,0, 9, 9, , , .95, 0, 0,0,,
  1420.7 1437.48    1469    1469    1519    1569    1569 1581.79    1602
    75.9   76.42    76.4   77.51   77.65   77.56   76.46   76.55      76
                              73   73.06   73.28
    1389 1405.48    1437    1437    1487    1537    1537 1549.79  1585.5
    76.3   76.42    76.4   77.51   77.65   77.56   76.46   76.55      76
                              73   73.06   73.28
Pier Skew, UpSta & Num, DnSta & Num=  ,1499, 2 ,1467, 2 , 0 , 0 , 0 ,,
    1.65    1.65
       0     100
    1.65    1.65
       0     100
Pier Skew, UpSta & Num, DnSta & Num=  ,1539, 2 ,1507, 2 , 0 , 0 , 0 ,,
    1.65    1.65
       0     100
    1.65    1.65
       0     100
BR Coef=-1 , 1 , 1 ,1.25, 0 ,,,.8,-1,2,0,
WSPro=,,,, 1 ,,,, 0 ,,,, 0 ,,,,-1 ,-1 ,-1 , 0 , 0 , 0 , 0 , 0
BC Design=,, 0 ,, 0 ,,,,,,

Type RM Length L Ch R = 1 ,6117    ,88.69,85.18,79.33
BEGIN DESCRIPTION:
6116.553  Survey
END DESCRIPTION:
XS GIS Cut Line= 6
      3059933.36     13825973.95     3058530.433    13825813.795
     3058021.823    13825775.081     3057487.017    13825626.207
     3057265.874    13825517.935     3056604.701    13825402.896
#Sta/Elev= 30
       0   74.67  574.57    74.3  634.96   75.84  695.35   75.88  906.71   74.76
 1238.85   76.89 1389.83   76.34 1404.93   76.05 1429.78   73.62 1483.28   58.78
 1488.14   58.65    1495   59.08 1543.45   73.87 1585.36   76.03 1947.38   74.56
 2024.98   75.09 2071.94   76.75 2134.22   74.72 2227.65   76.46 2274.36   75.61
 2392.13   76.98 2414.49   76.87 2430.06   74.43 2493.44   74.29 2544.49   75.81
 2609.93   73.91 2644.89   75.46 2693.85   73.74 2843.85   74.82 3394.61   74.39
#Mann= 3 , 0 , 0
       0     .08       0 1429.78     .04       0 1543.45      .1       0
#XS Ineff= 2 , 0
       0     937            1637       0
Permanent Ineff=
       T       T
Bank Sta=1429.78,1543.45
XS Rating Curve= 0
Exp/Cntr=.5,.3

Type RM Length L Ch R = 1 ,6031    ,147.98,136.57,116.12
BEGIN DESCRIPTION:
6031.371  Copied Survey
END DESCRIPTION:
XS GIS Cut Line= 6
      3059944.03     13825879.55     3058520.239    13825724.191
     3058354.943    13825725.115     3057631.031     13825574.11
     3057197.059     13825459.06     3056599.648     13825368.06
#Sta/Elev= 30
       0   74.94  645.34   75.12  901.85   72.81  962.21   75.02  992.39   81.44
 1015.64   83.99 1218.89   85.96 1369.61   84.24 1388.26   82.43 1432.24   74.28
 1446.38   72.35 1495.28   58.78 1500.14   58.65    1507   59.08 1555.45   73.87
 1656.45   76.04 1794.36   72.39 1870.97   74.55 1978.23   74.85 2008.88   72.77
  2024.2   74.05 2269.36      75 2501.27   73.79 2516.79   71.76 2551.13   75.24
  2597.2   76.33 2741.18   74.05 3220.74    75.1 3296.61   76.89 3390.53    74.3
#Mann= 3 , 0 , 0
       0     .08       0 1432.24     .04       0 1555.45      .1       0
#XS Ineff= 2 , 0
       0     938            1641       0
Permanent Ineff=
       T       T
Bank Sta=1432.24,1555.45
XS Rating Curve= 0
Exp/Cntr=.3,.1

Type RM Length L Ch R = 1 ,5895    ,623.53,651.17,692.84
BEGIN DESCRIPTION:
5894.800  Survey
END DESCRIPTION:
XS GIS Cut Line= 4
     3059959.766    13825740.434     3058507.118    13825577.868
      3058355.05    13825611.064     3056591.437    13825346.268
#Sta/Elev= 30
       0   74.43  208.86   75.35  268.93   73.63  661.37   75.04  963.24    74.1
 1008.52      83 1023.62   84.29 1109.62   87.06 1219.83   88.09 1400.96   84.43
 1431.14   80.19 1461.72   73.05 1473.74   72.89 1519.92   59.04 1527.35   58.14
    1536   58.57 1582.48   73.37 1687.55   75.94 1903.08    73.9 1973.12   74.44
 2044.51   72.32 2069.93   74.51 2297.45   75.37 2524.98   72.65 2570.48      75
 2722.73   74.45 2889.01   75.84 3192.37   74.77 3311.71   77.21 3400.75   74.21
#Mann= 3 , 0 , 0
       0     .08       0 1473.74     .04       0 1582.48      .1       0
#XS Ineff= 2 , 0
       0     947            1647       0
Permanent Ineff=
       T       T
Bank Sta=1473.74,1582.48
XS Rating Curve= 0
Exp/Cntr=.3,.1

Type RM Length L Ch R = 1 ,5244    ,385.63,363.78,341.56
BEGIN DESCRIPTION:
5243.626  Survey Deleted Sand/Rock Piles on Right Bank
END DESCRIPTION:
XS GIS Cut Line= 4
     3060204.084    13825277.859     3058474.914    13824952.533
     3058310.161    13824918.889     3056617.498    13824782.708
#Sta/Elev= 30
       0    74.2  673.19   73.55  780.03   73.82  810.56   74.96  841.09   75.02
  929.01   74.18 1004.21   74.93 1100.56   74.84  1191.8   73.78 1587.02   74.19
 1624.62   73.67 1662.22   74.14 1695.82   71.44 1737.42   74.01 1756.88   74.52
 1759.51   73.63 1787.82   73.14 1826.22   59.27 1834.87   58.03 1843.82   58.96
 1889.43   73.91 1970.46   75.23  2015.6   74.78 2151.04   76.04 2158.16   76.56
 2768.03   79.58 3294.72   76.51 3303.72   75.86  3565.6   75.84 3625.79   73.42
#Mann= 3 , 0 , 0
       0     .08       0 1787.82     .04       0 1889.43     .08       0
#XS Ineff= 2 , 0
       0    1215            2017       0
Permanent Ineff=
       T       T
Bank Sta=1787.82,1889.43
XS Rating Curve= 0
Exp/Cntr=.3,.1

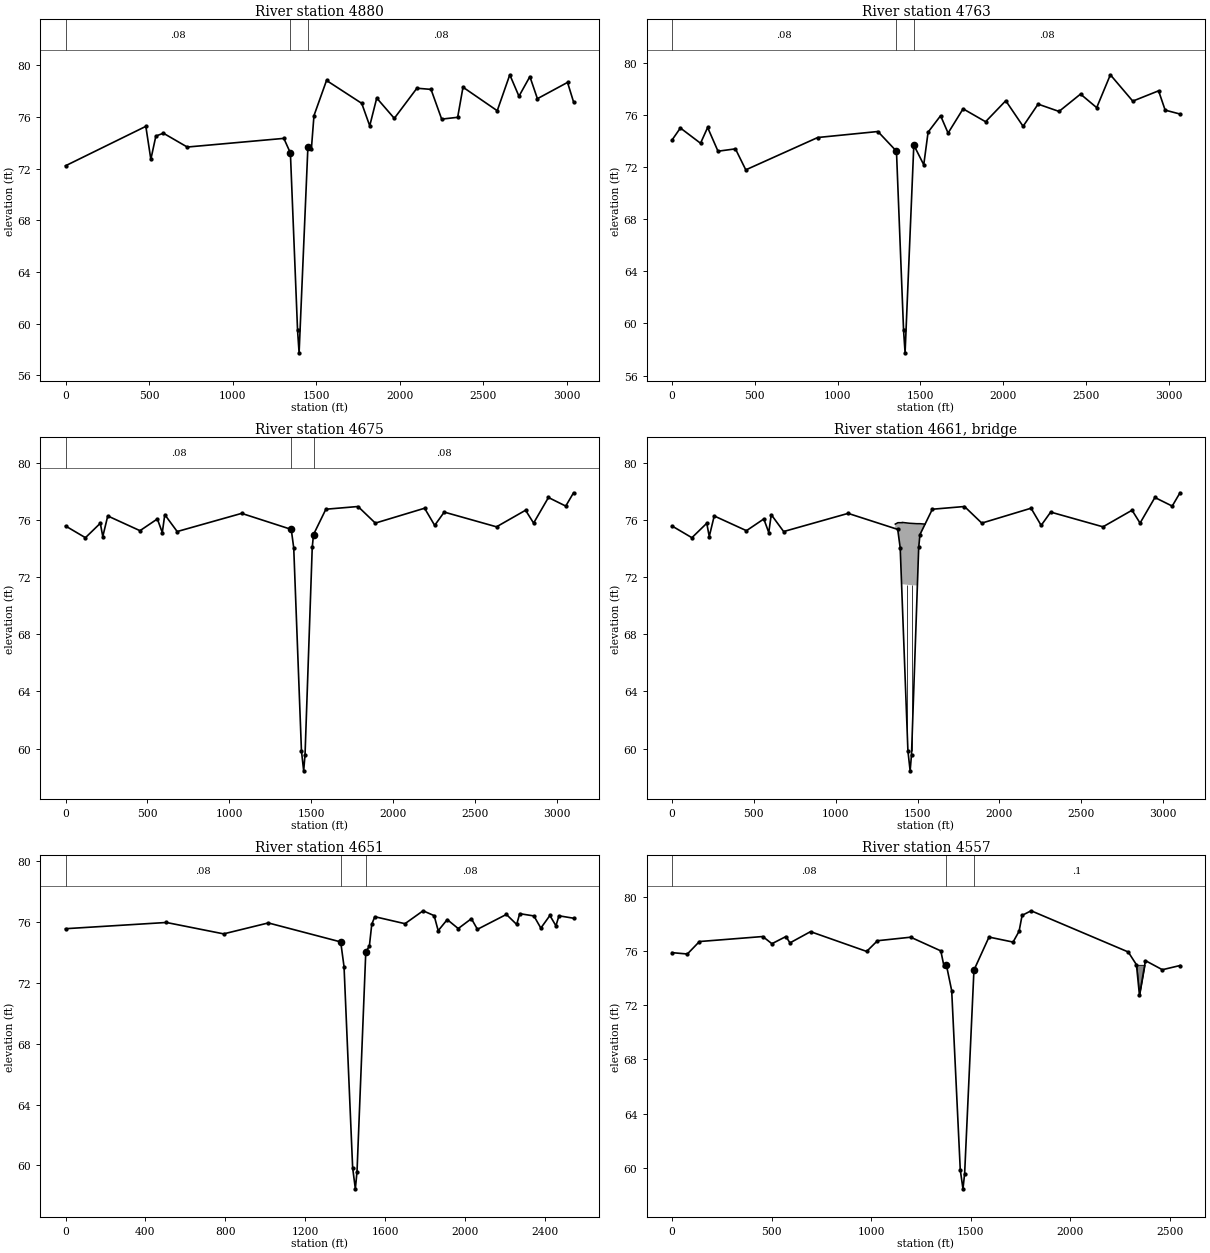
Type RM Length L Ch R = 1 ,4880    ,105.08,116.93,139.89
BEGIN DESCRIPTION:
4879.850  Survey
END DESCRIPTION:
XS GIS Cut Line= 4
     3059692.645    13824665.436     3058371.595    13824600.917
     3058223.056    13824609.549     3056656.589    13824518.845
#Sta/Elev= 30
       0   72.22  480.72   75.27  510.75   72.72  540.79   74.52  585.84   74.74
  728.62   73.67  1306.7   74.34 1345.93   73.21 1388.82   59.48 1397.98   57.75
 1450.73   73.68 1471.41   73.51    1487    76.1 1562.12   78.82 1772.85   77.05
  1820.7   75.31 1862.62   77.46  1967.8   75.89 2103.03   78.22 2187.52   78.13
 2251.31   75.83    2347   75.97  2378.9    78.3 2583.83   76.48 2658.96   79.26
 2713.82    77.6 2779.16   79.12 2824.23   77.41 3004.54   78.67 3040.51   77.16
#Mann= 3 , 0 , 0
       0     .08       0 1345.93     .04       0 1450.73     .08       0
#XS Ineff= 2 , 0
       0     740            1534       0
Permanent Ineff=
       T       T
Bank Sta=1345.93,1450.73
XS Rating Curve= 0
Exp/Cntr=.3,.1

Type RM Length L Ch R = 1 ,4763    ,85.02,87.96,85.41
BEGIN DESCRIPTION:
4762.919  Copied Survey
END DESCRIPTION:
XS GIS Cut Line= 6
      3059699.46     13824628.22     3058861.961     13824556.67
     3058341.096      13824484.7     3058317.158     13824487.45
     3057432.552     13824380.95     3056647.955     13824322.38
#Sta/Elev= 30
       0   74.06   50.74   74.99  172.59   73.82  215.35   75.03  277.97   73.21
  383.35   73.39  445.81   71.78  880.37   74.26 1243.69   74.72 1355.93   73.21
 1398.82   59.48 1407.98   57.75 1460.73   73.68 1520.78   72.17 1546.94   74.67
 1622.44   75.93 1667.74    74.6 1758.34   76.46 1894.25   75.47 2016.04   77.08
 2120.75   75.12 2211.35   76.82 2337.69   76.26 2467.73   77.59 2565.26   76.55
 2647.84   79.07 2783.21   77.05 2939.13   77.84 2978.75   76.36 3068.55   76.06
#Mann= 3 , 0 , 0
       0     .08       0 1355.93     .04       0 1460.73     .08       0
#XS Ineff= 2 , 0
       0     765            1555       0
Permanent Ineff=
       T       T
Bank Sta=1355.93,1460.73
XS Rating Curve= 0
Exp/Cntr=.5,.3

Type RM Length L Ch R = 1 ,4675    ,23.89,23.77,21.39
BEGIN DESCRIPTION:
4674.963  Copied Survey
END DESCRIPTION:
XS GIS Cut Line= 6
      3059738.03     13824595.72      3058353.35    13824401.566
     3058322.147     13824399.49     3058248.564     13824389.97
      3058231.92     13824387.95     3056660.161     13824201.63
#Sta/Elev= 30
       0   75.57  121.71   74.75  212.59   75.76  227.73   74.83  258.03   76.27
  454.93   75.24  560.96   76.06  591.25   75.11   606.4   76.36  682.13   75.18
 1075.94   76.45 1378.88   75.33 1394.03   74.04 1441.23   59.84 1454.75   58.45
 1463.12   59.58  1507.1   74.07 1514.84   74.97 1590.37   76.74 1786.73   76.93
 1892.47   75.77 2193.32   76.81 2254.99   75.61 2313.27   76.54 2632.61   75.51
 2810.23   76.67 2859.19   75.77 2949.82   77.56 3055.55   76.96 3103.22   77.89
#Mann= 3 , 0 , 0
       0     .08       0 1378.88     .04       0 1514.84     .08       0
#XS Ineff= 2 , 0
       0     826            1590       0
Permanent Ineff=
       T       T
Bank Sta=1378.88,1514.84
XS Rating Curve= 0
Exp/Cntr=.5,.3

Type RM Length L Ch R = 3 ,4661    ,,,
BEGIN DESCRIPTION:
Railroad Bridge
END DESCRIPTION:
Bridge Culvert--1,0,-1,-1, 0
Deck Dist Width WeirC Skew NumUp NumDn MinLoCord MaxHiCord MaxSubmerge Is_Ogee
2.77,20,2.6,0, 9, 9, , , .95, 0, 0,0,,
    1364    1380  1405.9    1406    1451    1496  1496.1    1515    1545
    75.7    75.8    75.8   75.82   75.76   75.73   75.73   75.73    75.7
                            71.5   71.44   71.41
    1120    1376  1401.9    1402    1447    1492  1492.1    1511    1534
    75.7    75.8    75.8   75.82   75.76   75.73   75.73   75.73    75.8
                            71.5   71.44   71.41
Pier Skew, UpSta & Num, DnSta & Num=  ,1437, 2 ,1433, 2 , 0 , 0 , 0 ,,
     1.5     1.5
       0     100
     1.5     1.5
       0     100
Pier Skew, UpSta & Num, DnSta & Num=  ,1464, 2 ,1460, 2 , 0 , 0 , 0 ,,
     1.5     1.5
       0     100
     1.5     1.5
       0     100
BR Coef=-1 , 1 , 1 ,1.05, 0 ,,,.8,-1,1.2,0,
WSPro=,,,, 1 ,,,, 0 ,,,, 0 ,,,,-1 ,-1 ,-1 , 0 , 0 , 0 , 0 , 0
BC Design=,, 0 ,, 0 ,,,,,,

Type RM Length L Ch R = 1 ,4651    ,91.74,93.95,93.99
BEGIN DESCRIPTION:
4651.196  Survey
END DESCRIPTION:
XS GIS Cut Line= 4
     3059741.509    13824570.966     3058377.218    13824381.078
     3058234.513    13824366.989     3057219.991    13824242.818
#Sta/Elev= 30
       0   75.57  504.98   75.98  791.57   75.23 1015.18   75.95 1377.44    74.7
 1394.17   73.07 1437.23   59.84 1450.75   58.45 1459.12   59.58  1503.1   74.07
 1520.84   74.41 1532.94   75.86 1548.06   76.36 1699.18    75.9 1789.85   76.75
 1845.17   76.43 1865.41   75.44 1910.74   76.17 1965.71   75.58 2031.64   76.23
 2061.86   75.53 2206.78   76.51 2258.32   75.85 2273.43   76.56 2344.53   76.41
 2379.21   75.61 2424.55   76.44 2454.77   75.76 2469.88   76.42 2542.94   76.26
#Mann= 3 , 0 , 0
       0     .08       0 1377.44     .04       0  1503.1     .08       0
#XS Ineff= 2 , 0
       0     835            1590       0
Permanent Ineff=
       T       T
Bank Sta=1377.44,1503.1
XS Rating Curve= 0
Exp/Cntr=.5,.3

Type RM Length L Ch R = 1 ,4557    ,116.48,108.64,103.56
BEGIN DESCRIPTION:
4557.250  Copied Survey
END DESCRIPTION:
XS GIS Cut Line= 6
        3059754.     13824481.84     3058404.649     13824292.71
     3058375.431    13824288.123     3058310.387    13824279.743
     3058266.727     13824276.33     3057225.289    13824152.818
#Sta/Elev= 30
       0   75.88   77.25   75.78  137.83    76.7  455.91   77.07  501.65   76.54
  572.11   77.07  592.23    76.6  695.42   77.43  977.27   75.97 1031.49   76.76
  1198.1   77.02 1349.56   76.01 1364.72   74.93 1377.06      75 1404.17   73.07
 1447.23   59.84 1460.75   58.45 1469.12   59.58 1515.82   74.59 1591.35   77.03
 1712.19   76.66  1742.4   77.46 1757.51   78.63 1802.82   78.97 2290.29   75.93
  2331.5   74.99  2346.6   72.75 2376.81   75.29 2461.66   74.62 2550.23   74.93
#Mann= 3 , 0 , 0
       0     .08       0 1377.06     .04       0 1515.82      .1       0
#XS Ineff= 2 , 0
       0     871            1581       0
Permanent Ineff=
       T       T
#Block Obstruct= 1 ,-1
 2330.81  2380.7   74.98
Bank Sta=1377.06,1515.82
XS Rating Curve= 0
Exp/Cntr=.3,.1