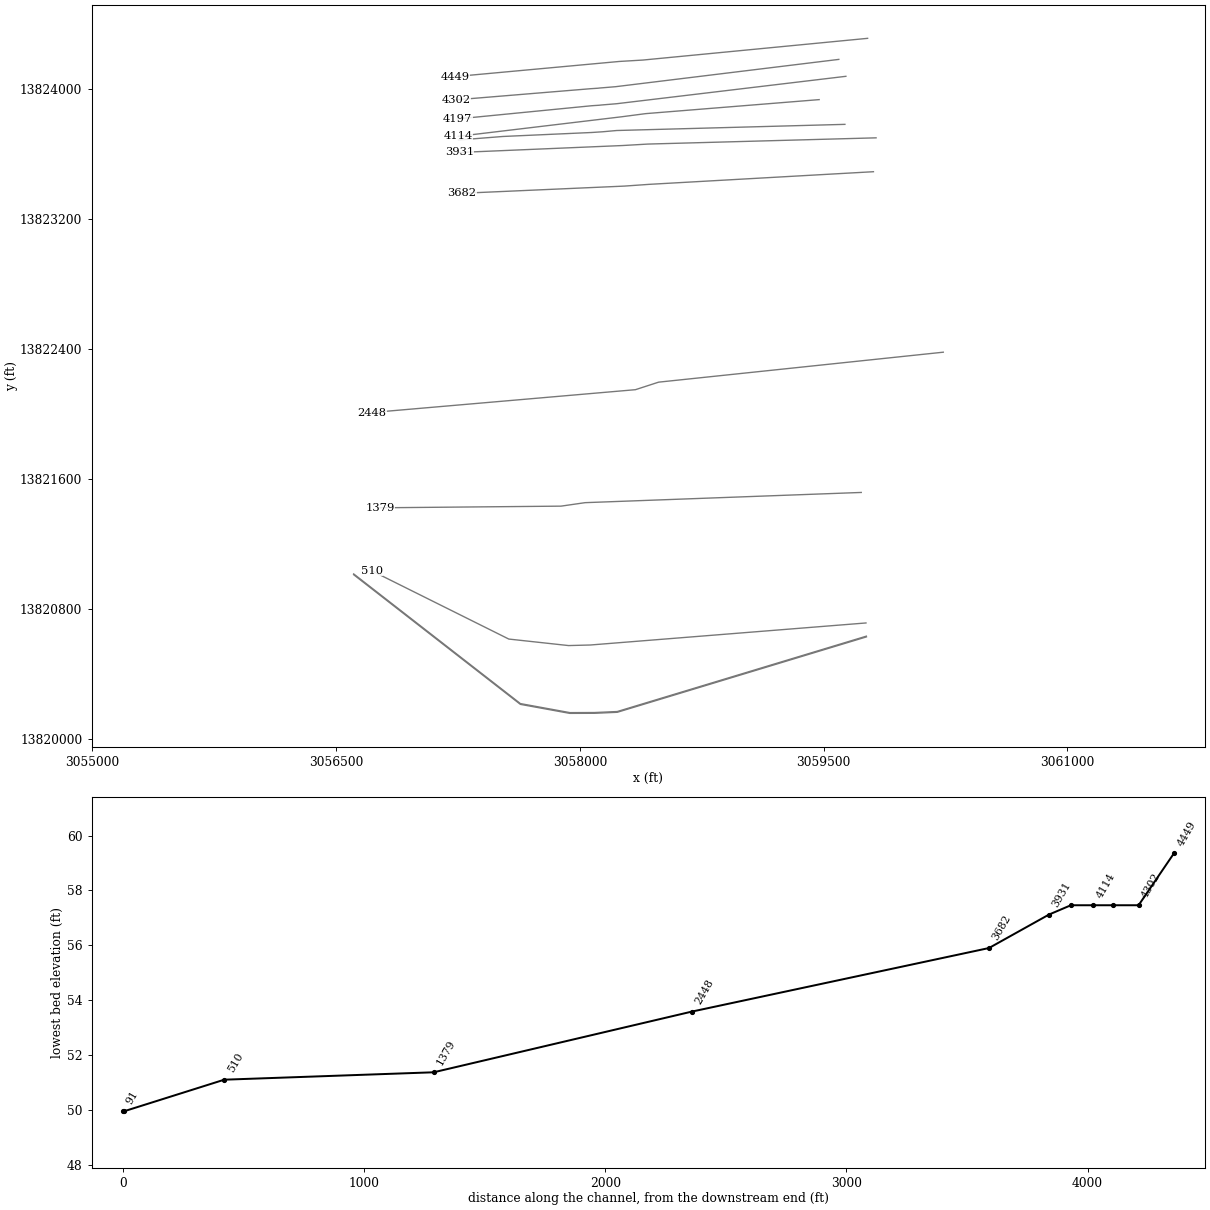
HEC-RAS study D124-00-00.prj: D124-00-00

--- D124-00-00.g01 (geometry) --- (continued)

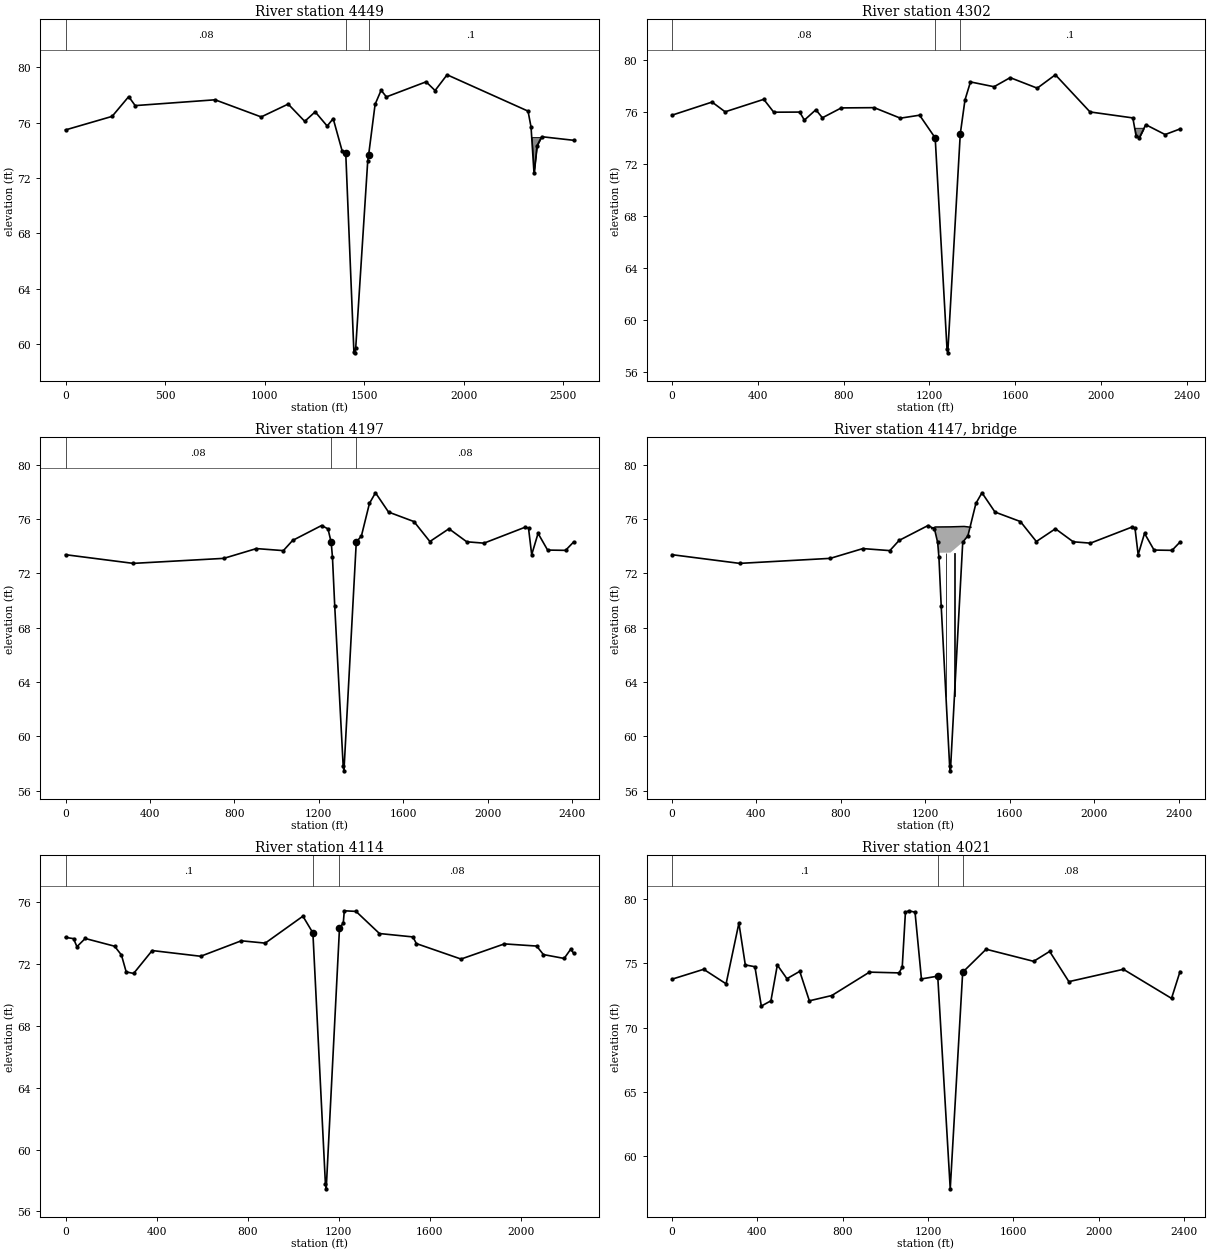
Type RM Length L Ch R = 1 ,4449    ,140.91,146.44,152.57
BEGIN DESCRIPTION:
4448.604  Survey
END DESCRIPTION:
XS GIS Cut Line= 4
     3059770.827     13824310.36     3058387.927    13824176.707
     3058242.261     13824168.04     3057229.889    13824074.669
#Sta/Elev= 30
       0   75.48  234.07   76.46  317.48   77.89  349.95   77.24  751.22   77.66
  982.89   76.42 1118.51   77.35 1201.64    76.1 1254.14   76.79 1314.42   75.76
 1344.56    76.3 1389.34   73.97  1407.7    73.8 1448.65    59.4 1452.56   59.35
 1457.67   59.69 1518.02   73.22 1522.27   73.63 1555.11   77.33 1585.24   78.35
 1611.84   77.87 1811.19   78.96 1856.39   78.33 1916.64   79.47 2323.36   76.84
 2338.42   75.69 2353.49   72.33 2368.55   74.34 2391.77   74.99 2551.94   74.73
#Mann= 3 , 0 , 0
       0     .08       0  1407.7     .04       0 1522.27      .1       0
#XS Ineff= 2 , 0
       0     922            1562       0
Permanent Ineff=
       T       T
#Block Obstruct= 1 ,-1
 2325.62 2403.97   74.96
Bank Sta=1407.7,1522.27
XS Rating Curve= 0
Exp/Cntr=.3,.1

Type RM Length L Ch R = 1 ,4302    ,105.8,105.49,105.04
BEGIN DESCRIPTION:
4302.167  Copied Survey
END DESCRIPTION:
XS GIS Cut Line= 6
      3059593.57     13824180.76     3058219.097     13824012.66
     3058119.487     13824004.39     3058110.433     13824003.26
      3058068.18     13824000.49      3057238.29    13823931.946
#Sta/Elev= 30
       0   75.75  186.88   76.76   247.9   76.01  427.92   76.97  474.58   75.98
  595.47   75.99  617.32   75.37  671.03   76.17  701.26   75.55  789.49   76.31
  943.04   76.33 1064.97   75.52 1154.61   75.75 1227.32      74 1282.33   57.78
  1285.9   57.46 1344.22    74.3 1366.17   76.92 1391.74   78.31 1501.74   77.94
 1576.95   78.64 1703.14   77.83 1787.67   78.86 1949.23      76 2148.89   75.54
 2163.95   74.16    2179   74.02  2209.1   75.02 2299.41   74.26 2368.85   74.69
#Mann= 3 , 0 , 0
       0     .08       0 1227.32     .04       0 1344.22      .1       0
#XS Ineff= 2 , 0
       0     793            1371       0
Permanent Ineff=
       T       T
#Block Obstruct= 1 ,-1
 2156.81 2198.77   74.78
Bank Sta=1227.32,1344.22
XS Rating Curve= 0
Exp/Cntr=.5,.3

Type RM Length L Ch R = 1 ,4197    ,84.85,82.78,84.61
BEGIN DESCRIPTION:
4196.674  Copied Survey
END DESCRIPTION:
XS GIS Cut Line= 6
      3059637.09     13824076.62     3058224.777     13823907.78
      3058130.39     13823899.94     3058120.585     13823898.71
     3058073.187      13823895.6     3057245.221    13823814.183
#Sta/Elev= 30
       0   73.38  320.82   72.74  749.77   73.11  904.19   73.83 1031.89   73.68
 1075.77   74.43 1213.04   75.53 1243.38   75.28 1258.49   74.28 1264.51   73.19
 1275.14   69.63 1315.33   57.78  1318.9   57.46 1377.22    74.3 1401.78   74.77
  1439.7   77.16 1468.29   77.94 1530.06   76.52 1650.52   75.82 1725.88   74.35
 1816.31   75.29 1900.53   74.33 1982.11   74.23 2178.05   75.41 2193.12   75.34
 2208.19   73.38 2238.34   74.95 2283.55   73.72 2368.58    73.7 2406.42   74.31
#Mann= 3 , 0 , 0
       0     .08       0 1258.49     .04       0 1377.22     .08       0
#XS Ineff= 2 , 0
       0     878            1421       0
Permanent Ineff=
       T       T
Bank Sta=1258.49,1377.22
XS Rating Curve= 0
Exp/Cntr=.5,.3

Type RM Length L Ch R = 3 ,4147    ,,,
BEGIN DESCRIPTION:
Harwin Road
END DESCRIPTION:
Bridge Culvert--1,0,-1,-1, 0
Deck Dist Width WeirC Skew NumUp NumDn MinLoCord MaxHiCord MaxSubmerge Is_Ogee
27.78,50,2.6,0, 5, 5, , , .95, 0, 0,0,,
    1230    1247    1318    1384    1416
    75.3   75.42   75.43   75.46    75.4
           73.52   73.53   73.56
    1043    1072    1143    1209    1225
      75   75.42   75.43   75.46   75.39
           73.52   73.53   73.56
Pier Skew, UpSta & Num, DnSta & Num=  ,1298, 2 ,1123, 2 , 0 , 0 , 0 ,,
     1.3     1.3
       0     100
     1.3     1.3
       0     100
Pier Skew, UpSta & Num, DnSta & Num=  ,1338, 2 ,1163, 2 , 0 , 0 , 0 ,,
     1.3     1.3
       0     100
     1.3     1.3
       0     100
BR Coef=-1 , 1 , 1 ,1.25, 0 ,,,.8,-1,2,0,
WSPro=,,,, 1 ,,,, 0 ,,,, 0 ,,,,-1 ,-1 ,-1 , 0 , 0 , 0 , 0 , 0
BC Design=,, 0 ,, 0 ,,,,,,

Type RM Length L Ch R = 1 ,4114    ,102.96,92.61,79.79
BEGIN DESCRIPTION:
4113.897  Survey
END DESCRIPTION:
XS GIS Cut Line= 4
      3059472.55     13823933.18     3058404.752     13823846.91
     3058256.445    13823827.497     3057251.511    13823707.323
#Sta/Elev= 30
       0   73.71   35.16   73.63   50.21   73.11   86.63   73.64  215.75   73.14
  245.85   72.57  266.72   71.48  299.46   71.38  380.97   72.86  594.15   72.49
  772.56   73.49   877.9   73.34 1043.44   75.08 1087.32      74 1142.33   57.78
  1145.9   57.46 1204.22    74.3 1220.85   74.64 1225.37   75.43 1276.84   75.39
  1379.8   73.96 1526.96   73.74 1542.07   73.31 1738.46   72.31 1928.88   73.29
 2070.81   73.15 2100.46    72.6 2191.66   72.35 2220.58   72.95 2232.94   72.69
#Mann= 3 , 0 , 0
       0      .1       0 1087.32     .04       0 1204.22     .08       0
#XS Ineff= 2 , 0
       0     747            1256       0
Permanent Ineff=
       T       T
Bank Sta=1087.32,1204.22
XS Rating Curve= 0
Exp/Cntr=.5,.3

Type RM Length L Ch R = 1 ,4021    ,88.55,90.7,93.19
BEGIN DESCRIPTION:
4021.282  Copied Survey
END DESCRIPTION:
XS GIS Cut Line= 6
      3059631.02     13823780.91     3058226.267     13823743.03
     3058139.784     13823735.25     3058073.085     13823730.86
     3057526.535     13823706.34     3057252.847    13823684.635
#Sta/Elev= 30
       0   73.76  148.57   74.53  253.61    73.4  313.63   78.12  343.64   74.87
  388.66   74.73  418.67   71.67  463.69   72.08   493.7   74.86  538.72    73.8
  598.74   74.37  643.75   72.08  748.79   72.49  925.39   74.31 1063.91   74.25
 1078.91   74.69 1093.92   78.95 1108.92   79.08 1138.93   78.97 1168.95   73.78
 1245.32      74  1303.9   57.46 1362.22    74.3 1472.06   76.09 1694.71   75.15
 1769.78   75.92 1859.87   73.57 2115.15   74.53 2340.86   72.27 2380.63   74.35
#Mann= 3 , 0 , 0
       0      .1       0 1245.32     .04       0 1362.22     .08       0
#XS Ineff= 2 , 0
       0     946            1406       0
Permanent Ineff=
       T       T
Bank Sta=1245.32,1362.22
XS Rating Curve= 0
Exp/Cntr=.3,.1

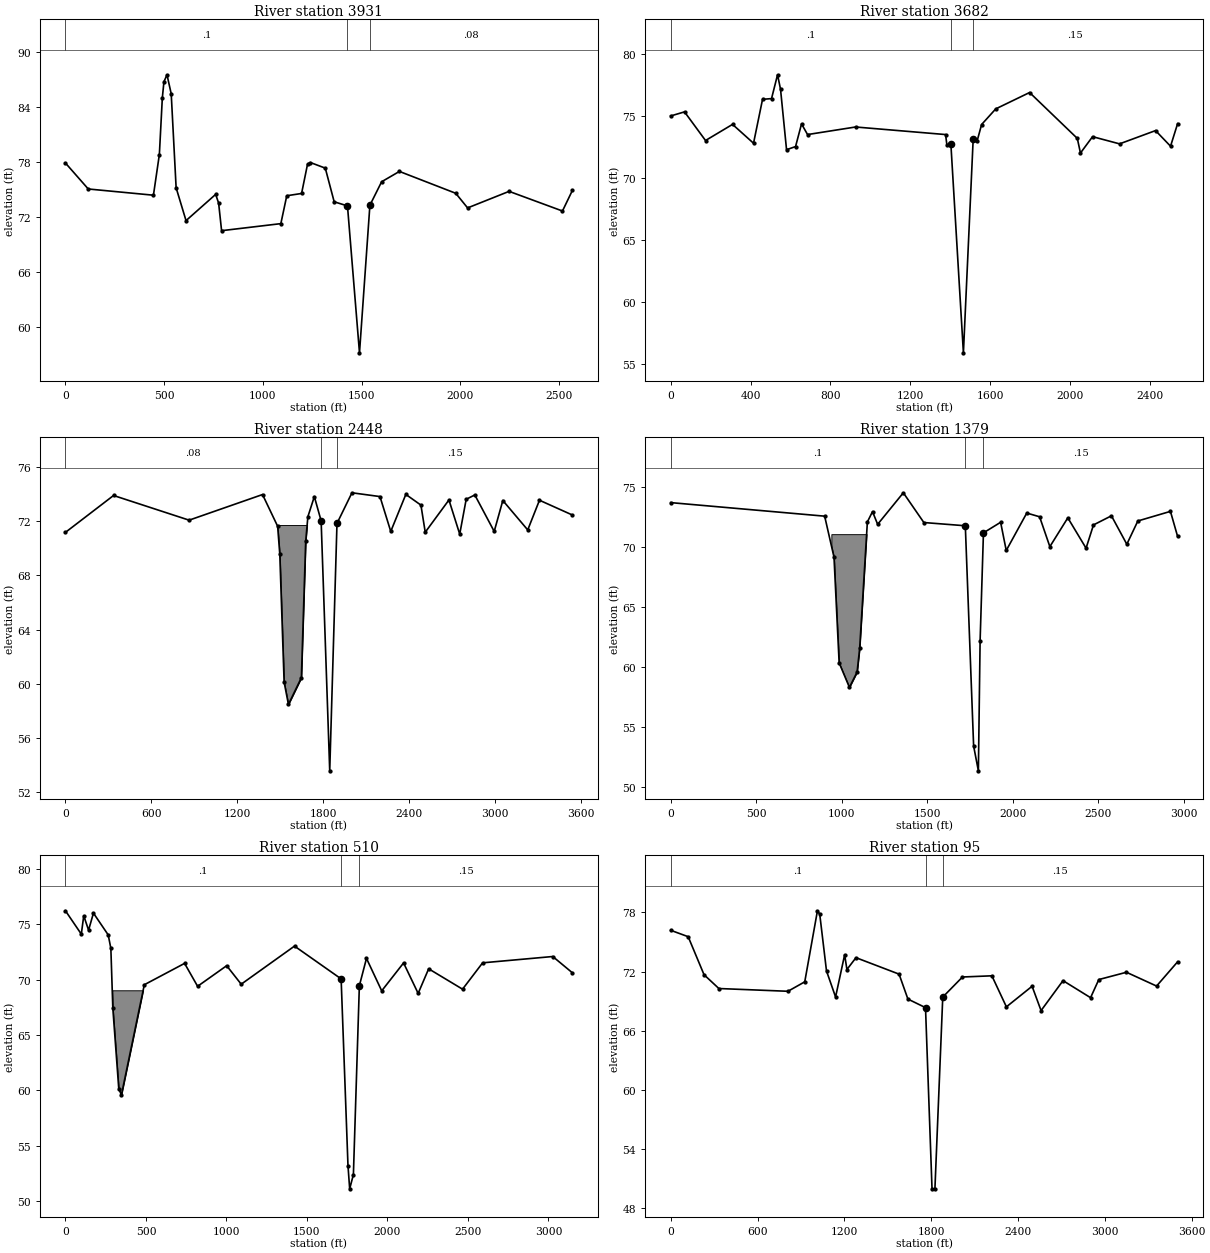
Type RM Length L Ch R = 1 ,3931    ,246.07,248.88,250.02
BEGIN DESCRIPTION:
3930.582  Survey
END DESCRIPTION:
XS GIS Cut Line= 4
     3059822.948    13823697.937      3058418.22     13823659.61
     3058264.848    13823650.696     3057257.359    13823607.972
#Sta/Elev= 30
       0   77.88  115.49   75.04  445.61   74.36  475.62   78.81  490.63      85
   498.8   86.77  514.23   87.53  535.65   85.45  560.51   75.17  610.68   71.58
  760.73   74.45  775.74    73.5  790.74   70.48 1090.85   71.25 1120.87    74.3
 1195.89   74.55  1225.9   77.74 1240.91   77.93 1315.94   77.32 1360.95   73.64
 1428.29   73.19 1489.15   57.12 1541.83   73.26 1601.27   75.83 1691.35   76.96
 1976.61   74.57 2036.66   72.97 2246.85   74.78 2517.09   72.63 2567.28   74.88
#Mann= 3 , 0 , 0
       0      .1       0 1428.29     .04       0 1541.83     .08       0
#XS Ineff= 2 , 0
       0    1163            1595       0
Permanent Ineff=
       T       T
Bank Sta=1428.29,1541.83
XS Rating Curve= 0
Exp/Cntr=.3,.1

Type RM Length L Ch R = 1 ,3682    ,1215.75,1233.51,1257.05
BEGIN DESCRIPTION:
3681.696  Survey
END DESCRIPTION:
XS GIS Cut Line= 4
      3059806.66    13823489.452     3058425.799     13823411.63
     3058274.889    13823400.982     3057272.156    13823356.589
#Sta/Elev= 30
       0      75   69.27   75.33  174.44   73.02  309.65   74.32  414.82    72.8
  459.89   76.34  504.96    76.4  535.01   78.32  550.03   77.15  580.08   72.28
  625.15   72.53  655.11   74.36  685.25    73.5  925.77   74.11 1376.34    73.5
 1383.05   72.64 1402.74   72.76 1465.61    55.9  1514.6   73.16 1534.34   72.99
 1556.75   74.31 1627.45   75.57 1796.98   76.89 2035.92   73.19 2051.63   72.01
 2112.29   73.33 2247.43   72.75  2427.6   73.82 2502.68   72.56 2538.05   74.38
#Mann= 3 , 0 , 0
       0      .1       0 1402.74     .04       0  1514.6     .15       0
#XS Ineff= 2 , 0
       0    1204            1540       0
Permanent Ineff=
       T       T
Bank Sta=1402.74,1514.6
XS Rating Curve= 0
Exp/Cntr=.3,.1

Type RM Length L Ch R = 1 ,2448    ,1045.94,1069.28,1009.21
BEGIN DESCRIPTION:
2448.190  Survey
END DESCRIPTION:
XS GIS Cut Line= 4
      3060236.66     13822378.62     3058484.465    13822194.221
     3058341.706    13822147.844     3056718.482    13822007.257
#Sta/Elev= 30
       0   71.17  336.01   73.89   863.9   72.07 1376.72   73.96  1482.3   71.62
 1497.38   69.55 1527.55   60.13 1557.71   58.48 1648.21   60.45 1678.38   70.51
 1693.46   72.32 1738.71   73.81 1786.16   72.02  1846.2   53.58  1896.9   71.83
 2001.51   74.09 2197.24   73.81 2272.53   71.24 2377.92   73.97 2483.31   73.18
 2513.42   71.18 2679.04   73.56 2754.32   71.04 2799.49   73.61 2859.72   73.93
 2995.22   71.24 3055.45   73.52 3229.43   71.35  3311.4   73.54 3541.28   72.45
#Mann= 3 , 0 , 0
       0     .08       0 1786.16     .04       0  1896.9     .15       0
#XS Ineff= 2 , 0
       0    1715            2060       0
Permanent Ineff=
       T       T
#Block Obstruct= 1 ,-1
 1479.63 1727.73   71.71
Bank Sta=1786.16,1896.9
XS Rating Curve= 0
Exp/Cntr=.3,.1

Type RM Length L Ch R = 1 ,1379    ,873.99,868.42,848.38
BEGIN DESCRIPTION:
1378.913  Survey
END DESCRIPTION:
XS GIS Cut Line= 4
     3059731.736    13821515.364     3058032.116    13821452.503
     3057883.897    13821431.083     3056770.604    13821420.894
#Sta/Elev= 30
       0   73.73  900.26    72.6  954.89   69.18  984.91   60.37 1044.95   58.33
 1089.98   59.61 1104.99   61.58 1150.02   72.12 1180.04   72.98 1210.06   71.92
 1360.17   74.55 1480.25   72.07 1722.66    71.8 1771.23   53.44 1799.02   51.37
 1809.09   62.21 1828.68   71.21 1929.08   72.09 1961.94   69.74 2081.95   72.86
 2156.95   72.55 2216.95   70.06 2321.96   72.46 2428.67   69.93 2471.96   71.87
 2576.97   72.63 2666.97   70.26 2731.45    72.2 2921.98      73 2963.88   70.91
#Mann= 3 , 0 , 0
       0      .1       0 1722.66     .04       0 1828.68     .15       0
#XS Ineff= 2 , 0
       0    1564            1847       0
Permanent Ineff=
       T       T
#Block Obstruct= 1 ,-1
  939.46 1206.73    71.1
Bank Sta=1722.66,1828.68
XS Rating Curve= 0
Exp/Cntr=.3,.1

Type RM Length L Ch R = 1 ,510     ,418.67,415.01,404.83
BEGIN DESCRIPTION:
510.490  Survey
END DESCRIPTION:
XS GIS Cut Line= 5
     3059760.756    13820712.077      3058064.29    13820576.429
      3057930.16    13820572.901     3057562.194    13820613.017
     3056718.482    13821033.243
#Sta/Elev= 30
       0   76.21   98.57    74.1  113.62   75.76  143.71   74.46  173.81      76
   265.7   74.03  282.06   72.81  294.19   67.43  331.12   60.16  347.48   59.57
  489.81   69.53  740.02   71.46  820.87   69.39 1001.44   71.25 1091.73   69.58
 1422.78   73.02 1712.39   70.06 1754.98   53.19 1765.51    51.1 1788.64   52.39
 1825.63   69.44 1869.85   71.91 1964.47   68.98 2100.27    71.5 2190.81   68.75
 2256.13   70.97  2466.6   69.13 2591.29   71.51 3026.98   72.08 3148.77   70.61
#Mann= 3 , 0 , 0
       0      .1       0 1712.39     .04       0 1825.63     .15       0
#XS Ineff= 2 , 0
       0    1685            1848       0
Permanent Ineff=
       T       T
#Block Obstruct= 1 ,-1
  290.49  553.42   69.03
Bank Sta=1712.39,1825.63
XS Rating Curve= 0
Exp/Cntr=.5,.3

Type RM Length L Ch R = 1 ,95      ,4.63,4.65,4.7
BEGIN DESCRIPTION:
95.478  Survey
END DESCRIPTION:
XS GIS Cut Line= 6
     3059763.146    13820630.843     3058229.985    13820166.901
     3058090.034     13820160.73     3057938.204    13820160.224
     3057633.849    13820215.764     3056607.714    13821013.869
#Sta/Elev= 30
       0   76.19  120.82   75.54  230.53   71.68  333.04   70.28  810.38      70
  926.49   70.96 1014.11   78.17 1030.07   77.82  1076.8   72.06 1139.49   69.42
 1202.17   73.71 1217.85   72.21 1280.53   73.41  1578.3   71.74 1639.34   69.21
 1760.96   68.34    1806   49.95    1826   49.95 1880.15   69.41 2016.43   71.45
 2219.57   71.57 2319.96   68.42 2497.49   70.51 2559.55   68.04 2711.27   71.08
  2901.6   69.35 2958.61   71.19 3149.52   71.93 3357.67   70.53 3503.09   72.99
#Mann= 3 , 0 , 0
       0      .1       0 1760.96     .04       0 1880.15     .15       0
#XS Ineff= 2 , 0
       0    1639            1941       0
Permanent Ineff=
       T       T
Bank Sta=1760.96,1880.15
XS Rating Curve= 0
Exp/Cntr=.5,.3

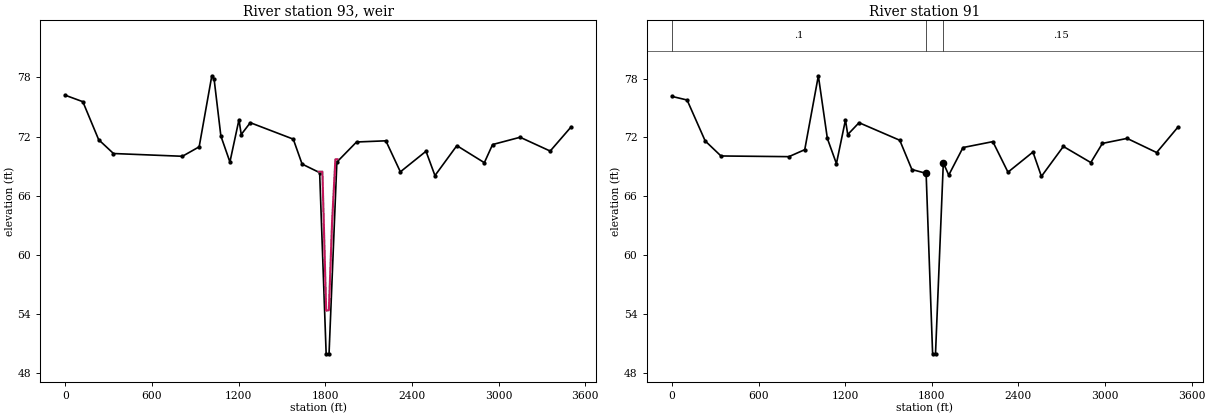
Type RM Length L Ch R = 5 ,93      ,,,
BEGIN DESCRIPTION:
Transition Structure near Mouth
END DESCRIPTION:
IW Pilot Flow=0
#Inline Weir SE= 7
    1754   68.44    1780   68.44    1806   54.34    1825   54.37    1847   63.29
    1870   69.69    1885    69.7
IW Dist,WD,Coef,Skew,MaxSub,Min_El,Is_Ogee,SpillHt,DesHd
2.3,1,3,0,.95,, 0 ,,,0,0,

Type RM Length L Ch R = 1 ,91      ,1.36,90.82,.93
BEGIN DESCRIPTION:
90.825  Copied Survey
END DESCRIPTION:
XS GIS Cut Line= 6
     3059763.279     13820626.33     3058229.686    13820162.256
     3058089.735    13820156.085     3057937.905     13820155.58
      3057633.55    13820211.119     3056607.415    13821009.224
#Sta/Elev= 30
       0   76.18  105.29   75.81  230.67   71.64     340   70.11  810.52   70.04
  920.22   70.75 1014.48   78.28 1076.94   71.89 1139.63   69.33 1202.31   73.78
 1217.99   72.29 1296.34    73.5 1578.44   71.71 1662.41   68.73 1760.96   68.34
    1806   49.95    1826   49.95 1880.15   69.41 1917.68   68.16 2016.58   70.97
 2223.12   71.57 2327.98   68.46 2501.04   70.51 2559.62   68.03 2711.65   71.08
 2901.67   69.44 2982.05   71.39 3153.07    71.9 3357.74   70.46 3503.54   73.02
#Mann= 3 , 0 , 0
       0      .1       0 1760.96     .04       0 1880.15     .15       0
#XS Ineff= 2 , 0
       0    1636            1945       0
Permanent Ineff=
       T       T
Bank Sta=1760.96,1880.15
XS Rating Curve= 0
Exp/Cntr=.5,.3

Chan Stop Cuts=-1

--- D124-00-00.g03 (geometry) ---

Version=Version 3.0.1  Mar 2001

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